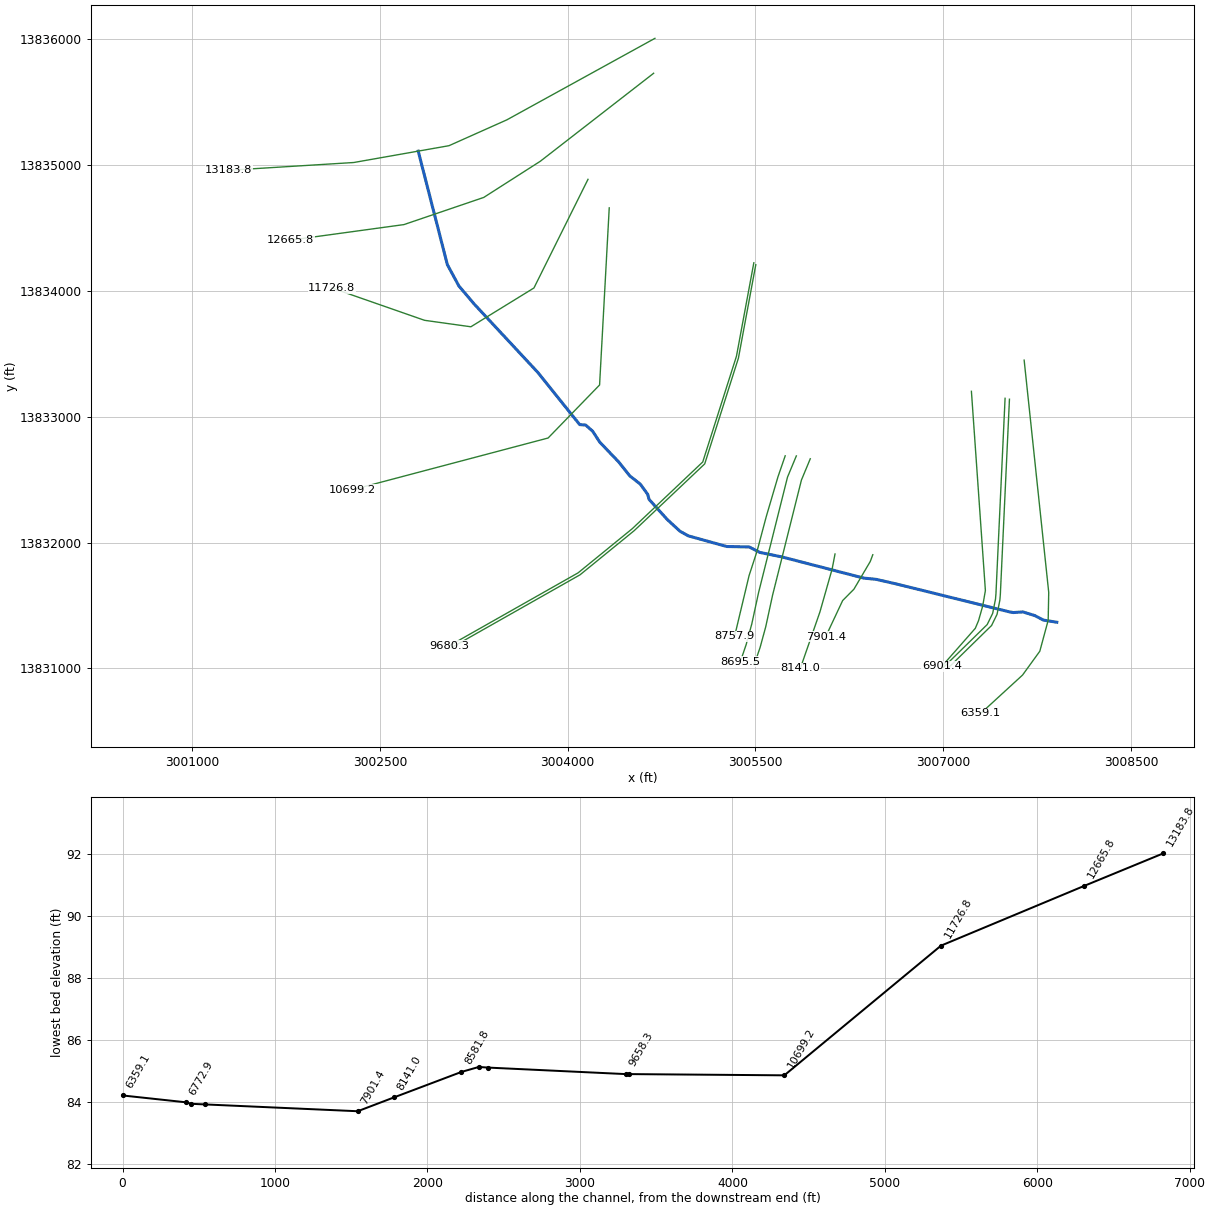
--- T103-00-00.PRJ (project) ---

Proj Title=T103-00-00
Current Plan=p02
Default Exp/Contr=.3,.1
English Units
Geom File=g01
Flow File=f01
Flow File=f02
Plan File=p01
Plan File=p02
Y Axis Title=Elevation
X Axis Title(PF)=Main Channel Distance
X Axis Title(XS)=Station
BEGIN DESCRIPTION:
HCFCD Unit T103-00-00
Flood Hazard Model
10, 2, 1, 0.2% Event
Filename T103-00-00.prj
Prepared by:  Watershed Concepts  Date:
Reviewed by:                      Date:
STATUS FINAL
END DESCRIPTION:
DSS Export Rating Curves= 0
DSS Export Rating Curve Sorted= 0
DSS Export Volume Flow Curves= 0
DXF OffsetX= 0
DXF OffsetY= 0
DXF ScaleX= 1
DXF ScaleY= 10

--- T103-00-00.p02 (plan) ---

Plan Title=Floodway
Version=Version 3.0.1  Mar 2001
Short Identifier=Floodway0607
Geom File=g01
Flow File=f02
Subcritical Flow
K Sum by GR= 0
Std Step Tol= 0.01
Critical Tol= 0.01
Num of Std Step Trials= 20
Max Error Tol= 0.3
Flow Tol Ratio= 0.001
Split Flow NTrial= 30
Split Flow Tol= 0.02
Split Flow Ratio= 0.02
Log Output Level= 0
Friction Slope Method= 1
Unsteady Friction Slope Method= 2
Parabolic Critical Depth
Global Vel Dist= 0 , 0 , 0
Global Log Level= 0
CheckData=True
Encroach Param=-1 ,0,0, 2
Encroach River=T103-00-00
Encroach Reach=Reach - 1
Encroach Node=13183.8
       1  4957.3  5055.6
Encroach Node=12665.8
       1  4947.2  5050.2
Encroach Node=11726.8
       1  4945.1  5055.2
Encroach Node=10699.2
       1  4929.6  5039.9
Encroach Node=9680.3
       1 4932.71 5038.41
Encroach Node=9669.3
       1 4932.71 5038.41
Encroach Node=9658.3
       1 4932.71 5038.41
Encroach Node=8757.9
       1  4927.4  5066.4
Encroach Node=8695.5
       1  4936.9  5055.5
Encroach Node=8638.6
       1  4936.9  5055.5
Encroach Node=8581.8
       1  4936.9  5055.5
Encroach Node=8141.0
       1    4944  5067.8
Encroach Node=7901.4
       1  4946.3  5054.6
Encroach Node=6901.4
       1    4940    5035
Encroach Node=6808.7
       1    4925    5040
Encroach Node=6790.8
       1    4925    5040
Encroach Node=6772.9
       1    4925    5040
Encroach Node=6359.1
       1    4910    5220
Encroach Reach=T103-00-00_0064
Encroach Node=13183.8
       1  4957.3  5055.6
Encroach Node=12665.8
       1  4947.2  5050.2
Encroach Node=11726.8
       1  4945.1  5055.2
Encroach Node=10699.2
       1  4929.6  5039.9
Encroach Node=9680.3
       1 4932.71 5038.41
Encroach Node=9669.3
       1 4932.71 5038.41
Encroach Node=9658.3
       1 4932.71 5038.41
Encroach Node=8757.9
       1  4927.4  5066.4
Encroach Node=8695.5
       1  4936.9  5055.5
Encroach Node=8638.6
       1  4936.9  5055.5
Encroach Node=8581.8
       1  4936.9  5055.5
Encroach Node=8141.0
       1    4944  5067.8
Encroach Node=7901.4
       1  4946.3  5054.6
Encroach Node=6901.4
       1    4940    5035
Encroach Node=6808.7
       1    4925    5040
Encroach Node=6790.8
       1    4925    5040
Encroach Node=6772.9
       1    4925    5040
Encroach Node=6359.1
       1    4910    5220
Computation Interval=1HOUR
Output Interval=1HOUR
Run HTab= 0
Run UNet= 0
Run PostProcess= 0
UNET Theta= 1
UNET ZTol= 0.02
UNET ZSATol= 0.1
UNET MxIter= 20
UNET MaxInSteps= 20
UNET DtIC= 0
UNET DtMin= 0
UNET MaxCRTS= 20
UNET WFStab= 2
UNET SFStab= 1
UNET WFX= 1
UNET SFX= 1
UNET Convert EG Bridges=-1
UNET Use Existing IB Tables=-1
Instantaneous Interval=1HOUR
Write IC File= 0
IC Time=0
Write Velocity= 0
Write Detailed= 0

--- T103-00-00.p01 (plan) ---

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Plan Title=FEMA Effective June 2007
Program Version=3.13
Short Identifier=FEMAeff0607
Geom File=g01
Flow File=f01
Unsteady Bridges Friction Slope Method= 1
Encroach Param=-1 ,0,0, 0
UNET Theta Warmup= 1
UNET DSS MLevel= 4
UNET DZMax Abort= 100
UNET Froude Reduction=False
UNET Froude Limit= 1
UNET Froude Power= 10
Echo Input=False
Echo Output=False
Detailed Automatic Start=False, 10

--- T103-00-00.f02 (steady flow) ---

Flow Title= Floodway
Program Version=3.13
Number of Profiles= 2
Profile Names=1PCT_100yr,1PCTFloodway_100yrFW
River Rch & RM=T103-00-00,T103-00-00_0064       ,13183.8
    1852    1852
River Rch & RM=T103-00-00,T103-00-00_0064       ,12665.8
    1875    1875
River Rch & RM=T103-00-00,T103-00-00_0064       ,11726.8
    1902    1902
River Rch & RM=T103-00-00,T103-00-00_0064       ,10699.2
    2150    2150
River Rch & RM=T103-00-00,T103-00-00_0064       ,6359.1
    3776    3776
Boundary for River Rch & Prof#=T103-00-00,T103-00-00_0064       , 1
Up Type= 0
Dn Type= 3
Dn Slope=0.00062
Boundary for River Rch & Prof#=T103-00-00,T103-00-00_0064       , 2
Up Type= 0
Dn Type= 3
Dn Slope=0.00062
DSS Import GetInterval= 0
DSS Import GetPeak= 0
DSS Import FillOption= 0

--- T103-00-00.f01 (steady flow) ---

Flow Title=FEMA Effective June 2007
Program Version=3.13
Number of Profiles= 4
Profile Names=10PCT_10yr,2PCT_50yr,1PCT_100yr,0.2PCT_500yr
River Rch & RM=T103-00-00,T103-00-00_0064       ,13183.8
     984    1551    1852    2736
River Rch & RM=T103-00-00,T103-00-00_0064       ,12665.8
     996    1570    1875    2769
River Rch & RM=T103-00-00,T103-00-00_0064       ,11726.8
    1011    1593    1902    2810
River Rch & RM=T103-00-00,T103-00-00_0064       ,10699.2
    1030    1801    2150    3176
River Rch & RM=T103-00-00,T103-00-00_0064       ,6359.1
    1997    3159    3776    5581
Boundary for River Rch & Prof#=T103-00-00,T103-00-00_0064       , 1
Up Type= 0
Dn Type= 3
Dn Slope=0.00062
Boundary for River Rch & Prof#=T103-00-00,T103-00-00_0064       , 2
Up Type= 0
Dn Type= 3
Dn Slope=0.00062
Boundary for River Rch & Prof#=T103-00-00,T103-00-00_0064       , 3
Up Type= 0
Dn Type= 3
Dn Slope=0.00062
Boundary for River Rch & Prof#=T103-00-00,T103-00-00_0064       , 4
Up Type= 0
Dn Type= 3
Dn Slope=0.00062
DSS Import GetInterval= 0
DSS Import GetPeak= 0
DSS Import FillOption= 0

--- T103-00-00.g01 (geometry) ---

Geom Title=T103-00-00 June 2007
Version=Version 3.0.1  Mar 2001

River Reach=T103-00-00      ,T103-00-00_0064
Reach XY= 30
      3002806.19     13835112.35      3003038.97     13834209.87
      3003131.25       13834040.      3003252.25       13833898.
      3003761.75       13833353.      3004096.12     13832938.21
      3004143.84     13832934.54       3004198.9     13832886.82
      3004257.06     13832798.32      3004408.14     13832640.87
      3004496.24     13832530.75      3004580.66     13832464.67
       3004639.4     13832383.91      3004650.52     13832343.81
       3004795.5       13832184.      3004898.25       13832090.
        3004963.       13832054.      3005270.78     13831969.11
      3005450.65     13831965.44      3005535.75       13831922.
        3005713.       13831886.      3006365.25       13831718.
       3006464.5       13831708.      3006619.25       13831673.
      3007526.75       13831450.       3007560.5       13831444.
      3007637.25       13831449.      3007732.25       13831420.
      3007801.25       13831384.        3007908.       13831367.

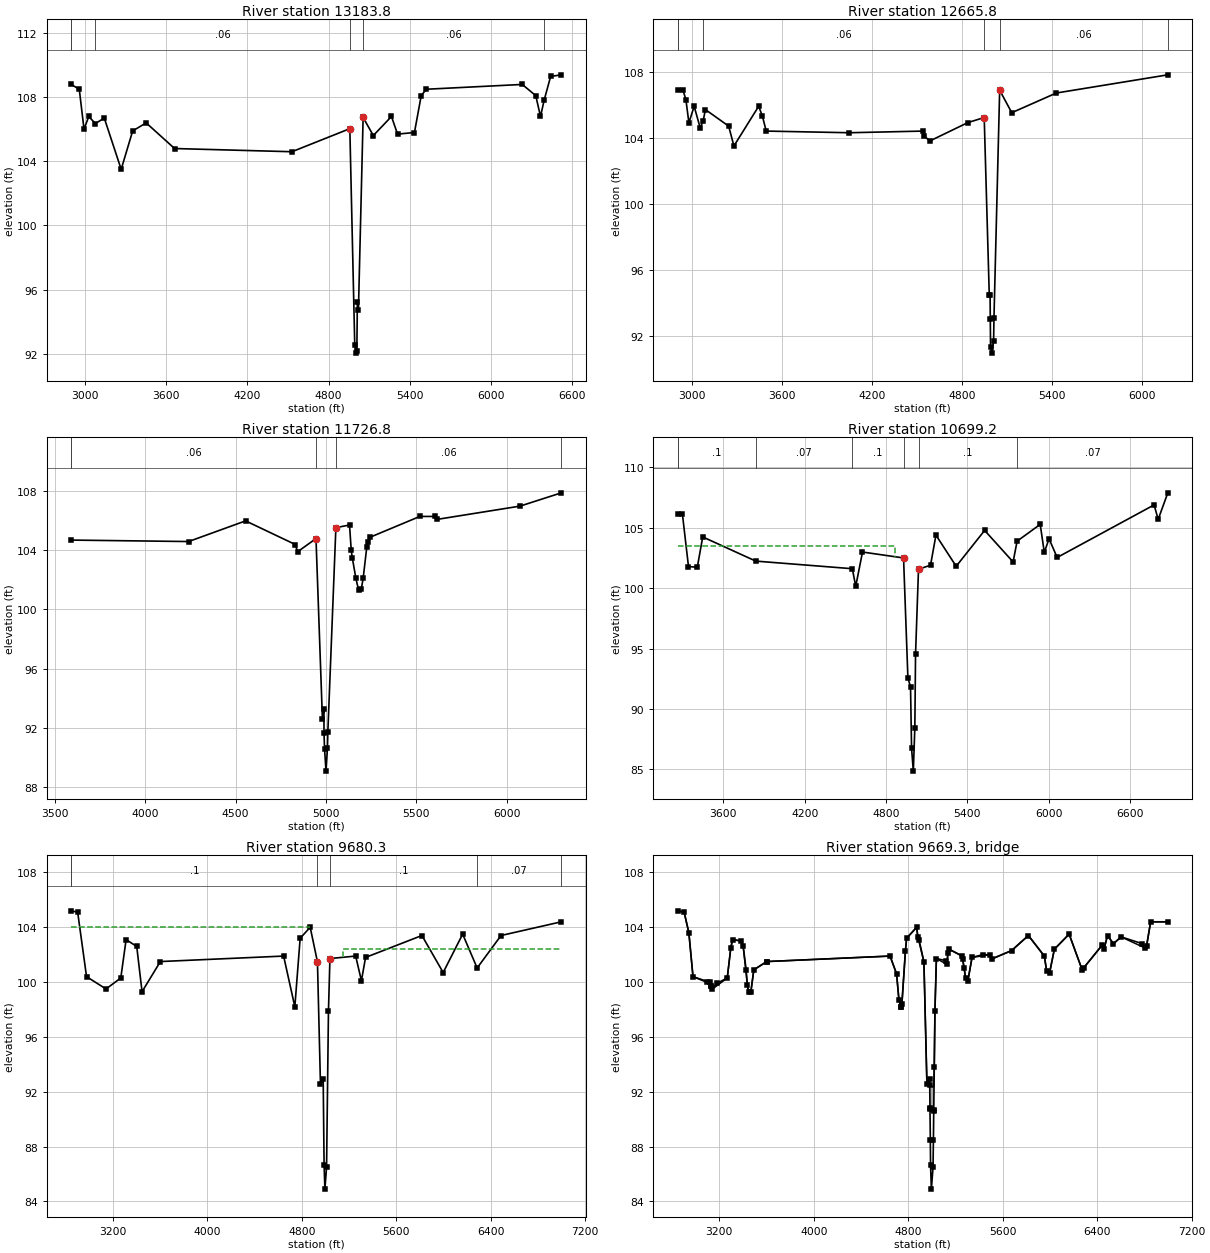
Type RM Length L Ch R = 1 ,13183.8 ,509.1,518,528
BEGIN DESCRIPTION:
Cross Section 13183.8
END DESCRIPTION:
XS GIS Cut Line= 5
      3004697.31     13836009.08      3003514.75     13835361.24
      3003052.01     13835155.58      3002291.06      13835021.9
       3001293.6      13834960.2
#Sta/Elev= 30
  2895.6   108.8  2955.6   108.5  2990.6     106  3025.6   106.8  3074.5  106.36
  3140.6   106.7  3265.6   103.5  3350.6   105.9  3450.6   106.4  3660.6   104.8
    4529   104.6  4957.3  106.04  4993.6   92.56  5002.8   92.03  5009.1   92.14
  5013.1   95.24    5021   94.75  5055.6  106.74  5131.1  105.61  5265.4   106.8
  5310.4   105.7  5435.4   105.8  5485.4   108.1    5523   108.5    6233   108.8
    6333   108.1    6368   106.8  6395.4  107.83    6443   109.3  6522.3   109.4
#Mann= 6 , 1 , 0
  2895.6      .2       0  2895.6      .1       0  3074.5     .06       0
  4957.3     .04       0  5055.6     .06       0  6395.4      .2       0
#XS Ineff= 2 , 0
       0  4957.3  106.04               0
Permanent Ineff=
       F       F
Bank Sta=4957.3,5055.6
XS Rating Curve= 0
Exp/Cntr=.3,.1

Type RM Length L Ch R = 1 ,12665.8 ,922.8,939,953.5
BEGIN DESCRIPTION:
Cross Section 12665.8
END DESCRIPTION:
XS GIS Cut Line= 5
      3004687.03     13835731.43      3003782.11     13835032.18
      3003329.65     13834744.25       3002692.1     13834528.31
      3001787.19     13834404.91
#Sta/Elev= 30
  2904.4   106.9  2939.4   106.9  2959.4   106.3  2979.4   104.9  3014.4   105.9
  3054.4   104.6  3074.2     105  3089.4   105.7  3244.4   104.7  3279.4   103.5
  3444.4   105.9  3469.4   105.3  3494.4   104.4    4048   104.3    4538   104.4
    4548   104.1  4584.3   103.8  4837.4  104.91  4947.2  105.22  4980.9   94.51
  4986.4    94.5  4987.7   93.06  4989.5   91.38  4997.8   90.98  5009.9   91.72
  5012.3   93.13  5050.2  106.87  5130.8  105.51  5427.4   106.7  6170.7   107.8
#Mann= 6 , 1 , 0
  2904.4      .2       0  2904.4      .1       0  3074.2     .06       0
  4947.2     .04       0  5050.2     .06       0  6170.7      .2       0
Bank Sta=4947.2,5050.2
XS Rating Curve= 0
Exp/Cntr=.3,.1

Type RM Length L Ch R = 1 ,11726.8 ,1005.2,1027.6,1044
BEGIN DESCRIPTION:
Cross Section 11726.8
END DESCRIPTION:
XS GIS Cut Line= 5
      3004162.59     13834888.22       3003730.7     13834024.43
      3003226.82     13833715.94      3002856.63     13833767.36
      3002116.25     13834024.43
#Sta/Elev= 29
  3589.6   104.7  4239.6   104.6  4555.3     106  4830.3   104.4  4843.4  103.91
  4945.1   104.8  4980.6   92.61  4989.2   93.28  4989.4   91.63  4992.3   90.58
  5000.6   89.05  5008.7   90.64  5010.7    91.7  5055.2  105.54  5130.7  105.72
  5140.3     104  5146.1   103.5  5166.1   102.1  5181.1   101.3  5196.1   101.4
  5206.1   102.1  5226.1   104.2  5231.1   104.6  5246.1   104.9  5519.9   106.3
  5604.9   106.3  5614.9   106.1  6074.9     107  6303.6   107.9
#Mann= 5 , 1 , 0
  3589.6      .2       0  3589.6     .06       0  4945.1     .04       0
  5055.2     .06       0  6303.6      .2       0
#XS Ineff= 2 , 0
       0                  5130.7       0  105.72
Permanent Ineff=
       F       F
Bank Sta=4945.1,5055.2
XS Rating Curve= 0
Exp/Cntr=.3,.1

Type RM Length L Ch R = 1 ,10699.2 ,1001.1,1018.9,1051.3
BEGIN DESCRIPTION:
Cross Section 10699.2
END DESCRIPTION:
XS GIS Cut Line= 4
       3004332.3     13834661.44      3004255.14      13833253.2
      3003843.81     13832831.59      3002280.78     13832420.27
#Sta/Elev= 30
  3263.3  106.13  3298.3  106.15  3343.3  101.79  3408.3  101.73  3448.3  104.24
  3839.6  102.24  4551.9  101.61  4576.8  100.15  4626.8  102.99  4929.6   102.5
  4961.8   92.56  4981.1   91.85  4988.7   86.76  5001.7   84.86  5012.9   88.45
  5018.1   94.54  5039.9  101.57  5128.6   101.9  5168.6  104.39  5317.7  101.81
  5527.7  104.78  5737.7  102.17  5767.1  103.89  5937.7  105.28  5967.7  102.96
  6002.7  104.09  6062.7  102.54  6777.7  106.89  6807.7  105.69  6878.9  107.89
#Mann= 7 , 1 , 0
  3263.3      .2       0  3263.3      .1       0  3839.6     .07       0
  4551.9      .1       0  4929.6     .04       0  5039.9      .1       0
  5767.1     .07       0
#XS Ineff= 2 , 0
       0  4863.6  103.52               0
Permanent Ineff=
       F       F
Bank Sta=4929.6,5039.9
XS Rating Curve= 0
Exp/Cntr=.5,.3

Type RM Length L Ch R = 1 ,9680.3  ,22,22,22
BEGIN DESCRIPTION:
Upstream Section of Bridge/Culvert/Weir
END DESCRIPTION:
XS GIS Cut Line= 6
      3005487.49     13834224.73      3005348.73     13833481.95
      3005079.37     13832641.21      3004516.16     13832110.65
      3004083.55     13831759.67      3003055.08     13831180.13
#Sta/Elev= 30
  2847.8   105.2  2902.8   105.1  2977.8   100.4  3142.8    99.5  3267.8   100.3
  3312.8   103.1  3402.8   102.6  3447.8    99.3  3602.8   101.5  4646.3   101.9
  4741.3    98.2  4786.3   103.2  4871.3     104 4932.71  101.48 4958.11   92.59
 4981.41   92.92 4988.91   86.68 4995.81    84.9 5009.91   86.49 5025.91   97.87
 5038.41  101.72  5256.3   101.9    5305   100.1    5340   101.8  5817.1   103.4
  5997.1   100.7  6162.1   103.5  6284.7  101.03  6487.1   103.4  6997.6   104.4
#Mann= 6 , 1 , 0
  2847.8      .2       0  2847.8      .1       0 4932.71     .04       0
 5038.41      .1       0  6284.7     .07       0  6997.6      .2       0
#XS Ineff= 2 , 0
       0    4871     104  5146.3       0   102.4
Permanent Ineff=
       F       F
Bank Sta=4932.71,5038.41
XS Rating Curve= 0
Exp/Cntr=.5,.3

Type RM Length L Ch R = 3 ,9669.3  ,,,
BEGIN DESCRIPTION:
PIPELINE
END DESCRIPTION:
Bridge Culvert--1,0,-1,-1, 0
Deck Dist Width WeirC Skew NumUp NumDn MinLoCord MaxHiCord MaxSubmerge Is_Ogee
10,2,2.6,0, 60, 60, , , .95, 0, 1,1,,
  2847.8  2902.8  2942.8  2977.8  3117.8  3142.8  3267.8  3297.8  3312.8  3387.8
  3402.8  3437.8  3447.8  3467.8  3492.8  3602.8  4646.3  4701.3  4721.3  4736.3
  4746.3  4776.3  4786.3  4871.3  4881.3 4932.71 4958.11 4981.41 4981.91 4984.21
  5015.9 5020.31 5025.91 5038.41  5126.3  5136.3  5146.3  5256.3    5285    5305
    5340    5490    5510    5675  5817.1  5952.1  5972.1  5997.1  6037.1  6162.1
  6272.1  6442.1  6457.1  6487.1  6537.1  6602.1  6802.1  6817.1  6852.1  6997.6
   105.2   105.1   103.6   100.4     100    99.5   100.3   102.5   103.1     103
   102.6    99.8    99.3    99.3   100.9   101.5   101.9   100.6    98.7    98.2
    98.4   102.3   103.2     104   103.3  101.48   92.59   92.92   92.54   92.44
   92.36    93.8   97.87  101.72   101.3   102.1   102.4   101.9   100.3   100.1
   101.8     102   101.7   102.3   103.4   101.9   100.8   100.7   102.4   103.5
   100.9   102.7   102.4   103.4   102.8   103.3   102.5   102.6   104.4   104.4
   105.2   105.1   103.6   100.4     100    99.5   100.3   102.5   103.1     103
   102.6    99.8    99.3    99.3   100.9   101.5   101.9   100.6    98.7    98.2
    98.4   102.3   103.2     104   103.3  101.48   92.59   92.92   92.53   90.77
   90.69   93.79   97.87  101.72   101.3   102.1   102.4   101.9   100.3   100.1
   101.8     102   101.7   102.3   103.4   101.9   100.8   100.7   102.4   103.5
   100.9   102.7   102.4   103.4   102.8   103.3   102.5   102.6   104.4   104.4
  2847.8  2902.8  2942.8  2977.8  3117.8  3142.8  3267.8  3297.8  3312.8  3387.8
  3402.8  3437.8  3447.8  3467.8  3492.8  3602.8  4646.3  4701.3  4721.3  4736.3
  4746.3  4776.3  4786.3  4871.3  4881.3 4932.71 4958.11 4981.41 4981.91 4984.21
  5015.9 5020.31 5025.91 5038.41  5126.3  5136.3  5146.3  5256.3    5285    5305
    5340    5490    5510    5675  5817.1  5952.1  5972.1  5997.1  6037.1  6162.1
  6272.1  6442.1  6457.1  6487.1  6537.1  6602.1  6802.1  6817.1  6852.1  6997.6
   105.2   105.1   103.6   100.4     100    99.5   100.3   102.5   103.1     103
   102.6    99.8    99.3    99.3   100.9   101.5   101.9   100.6    98.7    98.2
    98.4   102.3   103.2     104   103.3  101.48   92.59   92.92   92.54   92.44
   92.36    93.8   97.87  101.72   101.3   102.1   102.4   101.9   100.3   100.1
   101.8     102   101.7   102.3   103.4   101.9   100.8   100.7   102.4   103.5
   100.9   102.7   102.4   103.4   102.8   103.3   102.5   102.6   104.4   104.4
   105.2   105.1   103.6   100.4     100    99.5   100.3   102.5   103.1     103
   102.6    99.8    99.3    99.3   100.9   101.5   101.9   100.6    98.7    98.2
    98.4   102.3   103.2     104   103.3  101.48   92.59   92.92   92.53   90.77
   90.69   93.79   97.87  101.72   101.3   102.1   102.4   101.9   100.3   100.1
   101.8     102   101.7   102.3   103.4   101.9   100.8   100.7   102.4   103.5
   100.9   102.7   102.4   103.4   102.8   103.3   102.5   102.6   104.4   104.4
BR Coef= 1 , 1 , 0 ,1.25, 0 ,,,.8,0,2,0,
WSPro=,,,, 1 ,,,, 0 ,,,, 0 ,,,,-1 ,-1 ,-1 , 0 , 0 , 0 , 0 , 0
BR U #Sta/Elev= 81
  2847.8   105.2  2902.8   105.1  2942.8   103.6  2977.8   100.4  3092.8     100
  3117.8     100  3127.8    99.7  3132.8    99.7  3142.8    99.5  3177.8    99.9
  3267.8   100.3  3297.8   102.5  3312.8   103.1  3387.8     103  3402.8   102.6
  3427.8   100.9  3437.8    99.8  3447.8    99.3  3467.8    99.3  3492.8   100.9
  3602.8   101.5  3603.4   101.5  4646.3   101.9  4701.3   100.6  4721.3    98.7
  4736.3    98.2  4741.3    98.2  4746.3    98.4  4776.3   102.3  4786.3   103.2
  4871.3     104  4881.3   103.3 4890.91   103.1 4932.71  101.48 4958.11   92.59
 4981.41   92.92 4981.91   92.53 4984.12   90.79 4984.21   90.71 4987.01   88.51
 4988.91   86.68 4995.81    84.9 5009.91   86.49 5013.01   88.48  5015.9   90.58
 5016.01   90.66 5020.31   93.79 5025.91   97.87 5038.41  101.72 5119.91  101.56
  5126.3   101.3  5136.3   102.1  5146.3   102.4  5256.3   101.9    5260   101.7
    5275     101    5285   100.3    5305   100.1    5340   101.8    5430     102
    5490     102    5510   101.7    5675   102.3  5817.1   103.4  5952.1   101.9
  5972.1   100.8  5997.1   100.7  6037.1   102.4  6162.1   103.5  6272.1   100.9
  6284.7  101.03  6442.1   102.7  6457.1   102.4  6487.1   103.4  6537.1   102.8
  6602.1   103.3  6782.1   102.8  6802.1   102.5  6817.1   102.6  6852.1   104.4
  6997.6   104.4
BR U #Mann= 6
  2847.8      .2  2847.8      .1 4932.71    .045 5038.41      .1  6284.7     .07
  6997.6      .2
BR U Banks=4932.71,5038.41
BR D #Sta/Elev= 81
  2847.8   105.2  2902.8   105.1  2942.8   103.6  2977.8   100.4  3092.8     100
  3117.8     100  3127.8    99.7  3132.8    99.7  3142.8    99.5  3177.8    99.9
  3267.8   100.3  3297.8   102.5  3312.8   103.1  3387.8     103  3402.8   102.6
  3427.8   100.9  3437.8    99.8  3447.8    99.3  3467.8    99.3  3492.8   100.9
  3602.8   101.5  3603.4   101.5  4646.3   101.9  4701.3   100.6  4721.3    98.7
  4736.3    98.2  4741.3    98.2  4746.3    98.4  4776.3   102.3  4786.3   103.2
  4871.3     104  4881.3   103.3 4890.91   103.1 4932.71  101.48 4958.11   92.59
 4981.41   92.92 4981.91   92.53 4984.12   90.79 4984.21   90.71 4987.01   88.51
 4988.91   86.68 4995.81    84.9 5009.91   86.49 5013.01   88.48  5015.9   90.58
 5016.01   90.66 5020.31   93.79 5025.91   97.87 5038.41  101.72 5119.91  101.56
  5126.3   101.3  5136.3   102.1  5146.3   102.4  5256.3   101.9    5260   101.7
    5275     101    5285   100.3    5305   100.1    5340   101.8    5430     102
    5490     102    5510   101.7    5675   102.3  5817.1   103.4  5952.1   101.9
  5972.1   100.8  5997.1   100.7  6037.1   102.4  6162.1   103.5  6272.1   100.9
  6284.7  101.03  6442.1   102.7  6457.1   102.4  6487.1   103.4  6537.1   102.8
  6602.1   103.3  6782.1   102.8  6802.1   102.5  6817.1   102.6  6852.1   104.4
  6997.6   104.4
BR D #Mann= 6
  2847.8      .2  2847.8      .1 4932.71    .045 5038.41      .1  6284.7     .07
  6997.6      .2
BR D Banks=4932.71,5038.41
BC Design=,, 0 ,, 0 ,,,,,,
BC HTab HWMax=105.2

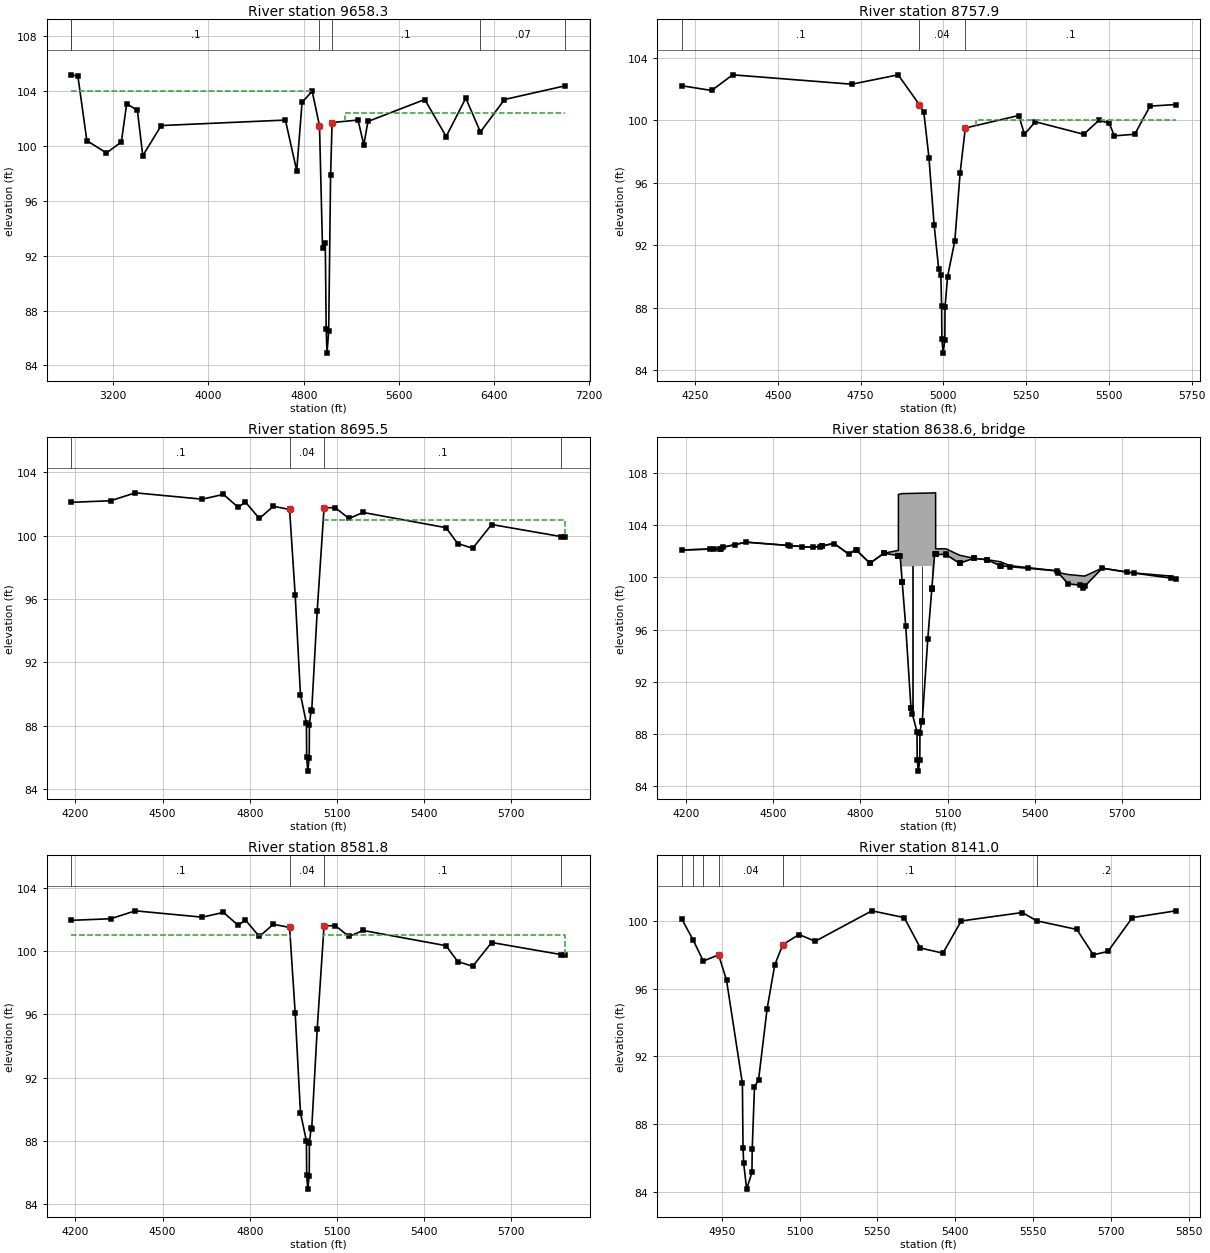
Type RM Length L Ch R = 1 ,9658.3  ,900.4,900.4,900.4
BEGIN DESCRIPTION:
Downstream Section of Bridge/Culvert/Weir
END DESCRIPTION:
XS GIS Cut Line= 6
      3005503.05     13834209.17      3005364.29     13833466.39
      3005094.93     13832625.65      3004531.72     13832095.09
      3004099.11     13831744.11      3003070.64     13831164.57
#Sta/Elev= 30
  2847.8   105.2  2902.8   105.1  2977.8   100.4  3142.8    99.5  3267.8   100.3
  3312.8   103.1  3402.8   102.6  3447.8    99.3  3602.8   101.5  4646.3   101.9
  4741.3    98.2  4786.3   103.2  4871.3     104 4932.71  101.48 4958.11   92.59
 4981.41   92.92 4988.91   86.68 4995.81    84.9 5009.91   86.49 5025.91   97.87
 5038.41  101.72  5256.3   101.9    5305   100.1    5340   101.8  5817.1   103.4
  5997.1   100.7  6162.1   103.5  6284.7  101.03  6487.1   103.4  6997.6   104.4
#Mann= 6 , 1 , 0
  2847.8      .2       0  2847.8      .1       0 4932.71     .04       0
 5038.41      .1       0  6284.7     .07       0  6997.6      .2       0
#XS Ineff= 2 , 0
       0    4871     104  5146.3       0   102.4
Permanent Ineff=
       F       F
Bank Sta=4932.71,5038.41
XS Rating Curve= 0
Exp/Cntr=.5,.3

Type RM Length L Ch R = 1 ,8757.9  ,61.4,62.45,66
BEGIN DESCRIPTION:
Cross Section 8757.9-Interpolated
END DESCRIPTION:
XS GIS Cut Line= 6
      3005738.09     13832690.04      3005680.35     13832523.23
      3005587.32     13832208.87      3005513.54       13831933.
      3005449.38     13831737.32      3005333.76      13831255.2
#Sta/Elev= 30
  4210.4   102.2  4300.2   101.9  4363.7   102.9  4723.7   102.3  4863.5   102.9
  4927.4     101  4941.1   100.5  4956.6    97.6  4972.2    93.3  4985.9    90.5
  4992.5    90.1  4994.8   88.14  4995.7      86  4999.4   85.11  5004.5   85.96
  5005.1   88.03  5012.8      90  5034.8    92.3  5050.6    96.6  5066.4    99.5
  5227.8   100.3  5245.1    99.1  5277.8    99.9    5424    99.1  5470.3     100
  5501.1    99.8  5516.5      99  5578.1    99.1  5624.3   100.9  5702.1     101
#Mann= 3 , 1 , 0
  4210.4      .1       0  4927.4     .04       0  5066.4      .1       0
#XS Ineff= 2 , 0
       0                    5098       0     100
Permanent Ineff=
       F       F
Bank Sta=4927.4,5066.4
XS Rating Curve= 0
Exp/Cntr=.5,.3

Type RM Length L Ch R = 1 ,8695.5  ,113.7,113.7,113.7
BEGIN DESCRIPTION:
Upstream Section of Bridge/Culvert/Weir
END DESCRIPTION:
XS GIS Cut Line= 6
      3005827.03     13832689.22      3005756.51     13832520.56
      3005525.43     13831602.66      3005470.87     13831352.32
      3005425.94     13831188.64      3005379.38     13831052.57
#Sta/Elev= 30
  4186.1   102.1  4321.1   102.2  4406.2   102.7  4636.2   102.3  4709.3   102.6
  4760.4  101.78  4784.5  102.13  4832.8  101.08  4881.1  101.85  4936.9  101.65
  4956.1   96.26  4974.3   89.96  4994.8   88.16  4995.7   86.02  4999.4   85.13
  5004.5   85.98  5005.1   88.05  5010.8   88.96  5012.9   88.91    5032   95.27
  5055.5  101.76  5094.3  101.76  5141.3  101.08  5189.9  101.46  5475.1   100.5
  5515.1    99.5    5567    99.2    5632   100.7  5870.4   99.94  5885.3    99.9
#Mann= 4 , 1 , 0
  4186.1      .1       0  4936.9     .04       0  5055.5      .1       0
  5870.4      .2       0
#XS Ineff= 2 , 0
       0  4939.2     101  5052.8       0     101
Permanent Ineff=
       F       F
Bank Sta=4936.9,5055.5
XS Rating Curve= 0
Exp/Cntr=.5,.3

Type RM Length L Ch R = 3 ,8638.6  ,,,
BEGIN DESCRIPTION:
FRY ROAD
Structure ID: T03-3
END DESCRIPTION:
Bridge Culvert--1,0,-1,-1, 0
Deck Dist Width WeirC Skew NumUp NumDn MinLoCord MaxHiCord MaxSubmerge Is_Ogee
10,93.7,2.6,0, 36, 36, , , .95, 0, 1,1,,
  4186.1  4321.1  4326.2  4406.2  4636.2  4709.3  4760.4  4784.5    4833  4881.1
 4930.89    4931  4936.9 4944.01  4944.1 5045.89    5046  5055.5    5059 5059.11
  5094.3  5141.3  5189.9  5235.6  5282.1  5315.6  5475.1  5480.6  5515.1    5557
    5567  5571.8    5632  5741.5  5870.4  5885.3
   102.1  102.21  102.31  102.71  102.31  102.61  101.79  102.14  101.09  101.86
  102.07  106.37   106.4  106.43  106.43  106.48  106.48  106.49  106.49  102.19
   102.2   101.7  101.47  101.36   101.2   100.9  100.51  100.37  100.22  100.13
  100.11   100.1  100.71  100.34   100.1    99.9
   102.1   102.2   102.3   102.7   102.3   102.6  101.78  102.13  101.08  101.85
  101.67  101.67  101.65   99.65  100.83  100.88   99.14  101.76  101.76  101.76
  101.76  101.08  101.46  101.35  100.89  100.82   100.5  100.36    99.5    99.4
    99.2   99.31   100.7  100.33   99.94    99.9
  4186.1  4321.1  4326.2  4406.2  4636.2  4709.3  4760.4  4784.5    4833  4881.1
 4930.89    4931  4936.9 4944.01  4944.1 5045.89    5046  5055.5    5059 5059.11
  5094.3  5141.3  5189.9  5235.6  5282.1  5315.6  5475.1  5480.6  5515.1    5557
    5567  5571.8    5632  5741.5  5870.4  5885.3
   102.1  102.21  102.31  102.71  102.31  102.61  101.79  102.14  101.09  101.86
  102.07  106.37   106.4  106.43  106.43  106.48  106.48  106.49  106.49  102.19
   102.2   101.7  101.47  101.36   101.2   100.9  100.51  100.37  100.22  100.13
  100.11   100.1  100.71  100.34   100.1    99.9
  101.96  102.06  102.16  102.56  102.16  102.46  101.64  101.99  100.94  101.71
  101.53  101.53  101.51   99.51  100.69  100.74      99  101.62  101.62  101.62
  101.62  100.94  101.32  101.21  100.75  100.68  100.36  100.22   99.36   99.26
   99.06   99.17  100.56  100.19    99.8   99.76
Pier Skew, UpSta & Num, DnSta & Num=  ,4979.1, 2 ,4979.1, 2 , 0 , 0 , 0 ,,
     1.4     1.4
   88.44  101.85
     1.4     1.4
    88.3  101.71
Pier Skew, UpSta & Num, DnSta & Num=  ,5012.9, 2 ,5012.9, 2 , 0 , 0 , 0 ,,
     1.4     1.4
   87.93  101.86
     1.4     1.4
   87.79  101.72
Abutment Skew #Up #Dn= , 2 , 2
  4943.9  4974.4
  100.83   89.95
  4943.9  4974.4
  100.69   89.81
Abutment Skew #Up #Dn= , 2 , 2
  5010.8 5046.09
   88.96  100.88
  5010.8 5046.09
   88.82  100.74
BR Coef= 1 , 1 , 0 ,1.25, 0 ,,,.8,0,2,0,
WSPro=,,,, 1 ,,,, 0 ,,,, 0 ,,,,-1 ,-1 ,-1 , 0 , 0 , 0 , 0 , 0
BR U #Sta/Elev= 73
  4186.1   102.1  4282.6  102.17  4297.6  102.18  4317.6   102.2  4321.1   102.2
  4326.2   102.3  4368.9  102.51  4406.2   102.7  4549.6  102.45  4559.6  102.43
  4599.6  102.36  4636.2   102.3  4659.6  102.37  4669.3   102.4  4669.6   102.4
  4709.3   102.6  4760.4  101.78  4784.5  102.13  4787.4  102.07  4832.8  101.08
    4833  101.08  4881.1  101.85  4881.9  101.85 4930.89  101.67    4931  101.67
 4931.11  101.67  4936.9  101.65  4943.9   99.68 4944.01   99.65  4944.1   99.63
  4956.1   96.26  4974.3   89.96  4974.4   89.95  4979.1    89.5  4994.8   88.16
  4995.7   86.02  4999.4   85.13  5004.5   85.98  5005.1   88.05  5010.7   88.94
  5010.8   88.96  5012.9   88.91    5032   95.27 5045.89   99.11    5046   99.14
  5046.1   99.16  5055.5  101.76 5058.89  101.76    5059  101.76 5059.11  101.76
  5094.3  101.76  5095.4  101.74  5141.3  101.08  5142.6  101.09  5189.4  101.46
  5189.9  101.46  5235.6  101.35  5236.7  101.34  5282.1  100.89  5282.5  100.89
  5315.6  100.82  5375.6   100.7  5475.1   100.5  5480.6  100.36  5515.1    99.5
    5557    99.4    5567    99.2  5571.8   99.31    5632   100.7  5716.6   100.4
  5741.5  100.33  5870.4   99.94  5885.3    99.9
BR U #Mann= 4
  4186.1      .1  4936.9     .04  5055.5      .1  5870.4      .2
BR U Banks=4936.9,5055.5
BR D #Sta/Elev= 73
  4186.1  101.96  4282.6  102.03  4297.6  102.04  4317.6  102.06  4321.1  102.06
  4326.2  102.16  4368.9  102.37  4406.2  102.56  4549.6  102.31  4559.6  102.29
  4599.6  102.22  4636.2  102.16  4659.6  102.23  4669.3  102.26  4669.6  102.26
  4709.3  102.46  4760.4  101.64  4784.5  101.99  4787.4  101.93  4832.8  100.94
    4833  100.94  4881.1  101.71  4881.9  101.71 4930.89  101.53    4931  101.53
 4931.11  101.53  4936.9  101.51  4943.9   99.54 4944.01   99.51  4944.1   99.49
  4956.1   96.12  4974.3   89.82  4974.4   89.81  4979.1   89.36  4994.8   88.02
  4995.7   85.88  4999.4   84.99  5004.5   85.84  5005.1   87.91  5010.7    88.8
  5010.8   88.82  5012.9   88.77    5032   95.13 5045.89   98.97    5046      99
  5046.1   99.02  5055.5  101.62 5058.89  101.62    5059  101.62 5059.11  101.62
  5094.3  101.62  5095.4   101.6  5141.3  100.94  5142.6  100.95  5189.4  101.32
  5189.9  101.32  5235.6  101.21  5236.7   101.2  5282.1  100.75  5282.5  100.75
  5315.6  100.68  5375.6  100.56  5475.1  100.36  5480.6  100.22  5515.1   99.36
    5557   99.26    5567   99.06  5571.8   99.17    5632  100.56  5716.6  100.26
  5741.5  100.19  5870.4    99.8  5885.3   99.76
BR D #Mann= 4
  4186.1      .1  4936.9     .04  5055.5      .1  5870.4      .2
BR D Banks=4936.9,5055.5
BC Design=,, 0 ,, 0 ,,,,,,
BC HTab HWMax=102.7

Type RM Length L Ch R = 1 ,8581.8  ,440.75,440.75,440.75
BEGIN DESCRIPTION:
Downstream Section of Bridge/Culvert/Weir
END DESCRIPTION:
XS GIS Cut Line= 6
      3005938.46     13832666.59      3005867.93     13832497.92
      3005636.85     13831580.02      3005582.29     13831329.68
      3005537.36       13831166.      3005490.81     13831029.94
#Sta/Elev= 30
  4186.1  101.94  4321.1  102.04  4406.2  102.54  4636.2  102.14  4709.3  102.44
  4760.4  101.62  4784.5  101.97  4832.8  100.92  4881.1  101.69  4936.9  101.49
  4956.1    96.1  4974.3    89.8  4994.8      88  4995.7   85.86  4999.4   84.97
  5004.5   85.82  5005.1   87.89  5010.8    88.8  5012.9   88.75    5032   95.11
  5055.5   101.6  5094.3   101.6  5141.3  100.92  5189.9   101.3  5475.1  100.34
  5515.1   99.34    5567   99.04    5632  100.54  5870.4   99.78  5885.3   99.74
#Mann= 4 , 1 , 0
  4186.1      .1       0  4936.9     .04       0  5055.5      .1       0
  5870.4      .2       0
#XS Ineff= 2 , 0
       0  4939.2     101  5052.8       0     101
Permanent Ineff=
       F       F
Bank Sta=4936.9,5055.5
XS Rating Curve= 0
Exp/Cntr=.5,.3

Type RM Length L Ch R = 1 ,8141.0  ,257.4,239.6,226
BEGIN DESCRIPTION:
Cross Section 8141.0-Interpolated
END DESCRIPTION:
XS GIS Cut Line= 4
       3006136.1     13831909.69      3006113.19     13831790.57
      3006015.37     13831448.21      3005858.93      13831000.2
#Sta/Elev= 30
  4873.3   100.1  4894.9   98.88  4914.5   97.63    4944      98  4959.3    96.5
  4989.9    90.4  4991.1   86.56  4992.4   85.67  4998.1   84.15  5008.3   85.14
  5008.8    86.5  5013.2    90.2    5021    90.6  5037.5    94.8  5052.2    97.4
  5067.8    98.6    5099    99.2  5130.2    98.8  5239.4   100.6  5301.8   100.2
    5333    98.4  5376.4    98.1  5411.7     100  5529.5   100.5  5557.1  100.01
  5634.5    99.5  5666.3      98  5694.4    98.2  5741.5   100.2  5825.2   100.6
#Mann= 6 , 1 , 0
  4873.3      .1       0  4894.9     .07       0  4914.5      .1       0
    4944     .04       0  5067.8      .1       0  5557.1      .2       0
Bank Sta=4944,5067.8
XS Rating Curve= 0
Exp/Cntr=.3,.1

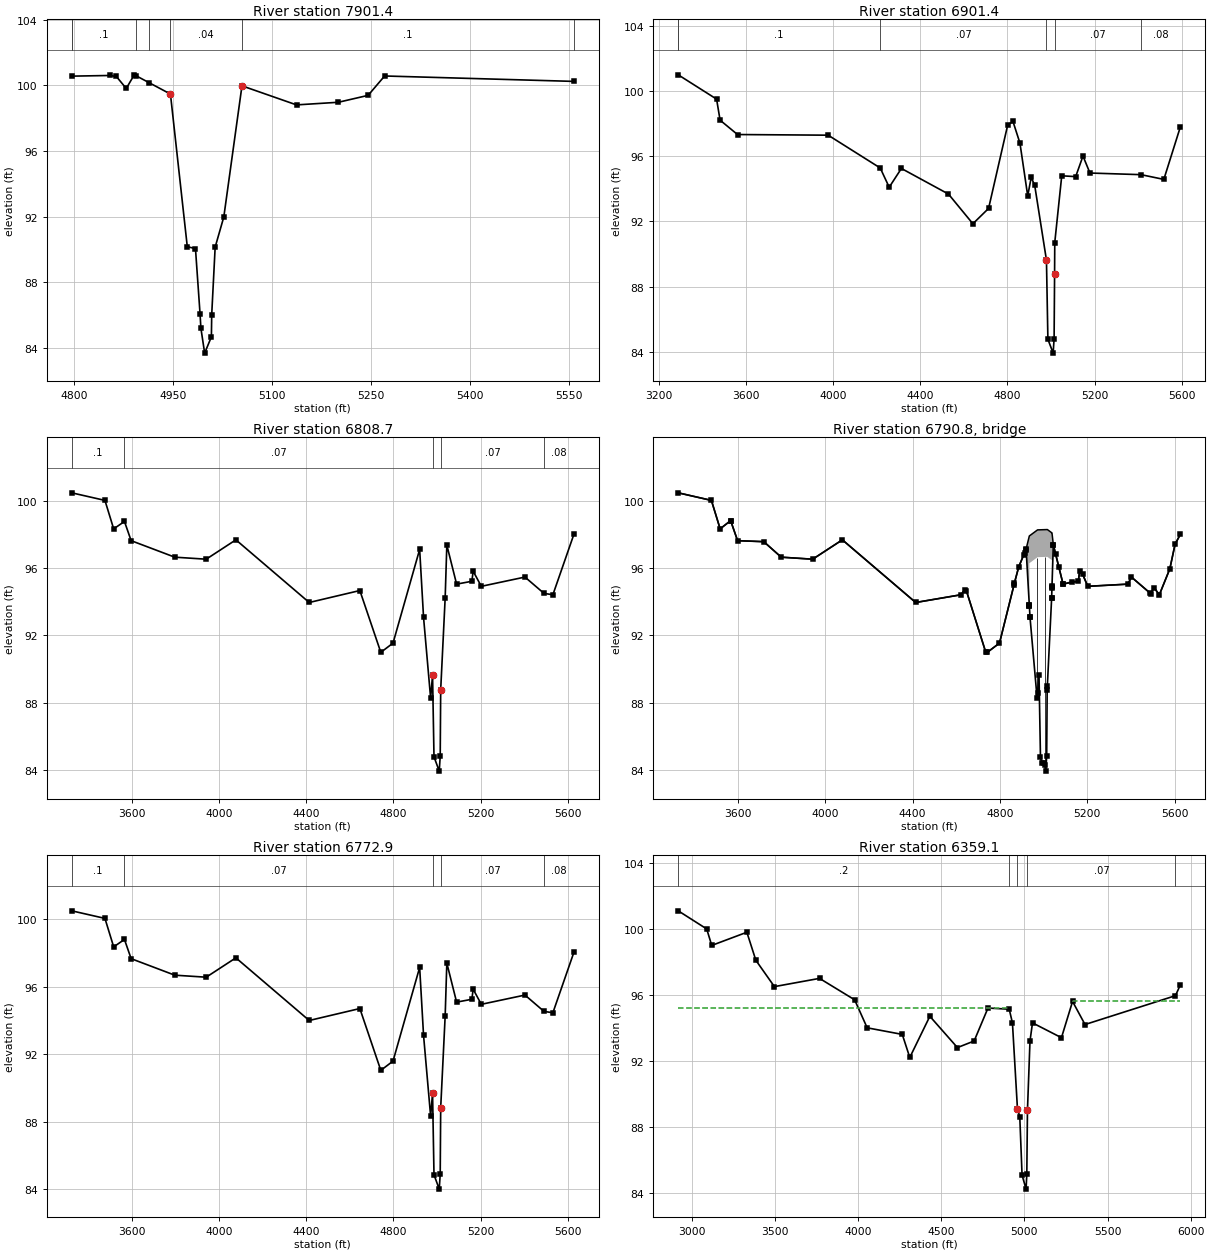
Type RM Length L Ch R = 1 ,7901.4  ,980.3,1000,953.2
BEGIN DESCRIPTION:
Cross Section 7901.4
END DESCRIPTION:
XS GIS Cut Line= 5
      3006437.89     13831903.65      3006417.63     13831849.84
      3006287.03     13831629.45      3006197.24     13831539.66
       3006060.8     13831250.71
#Sta/Elev= 23
  4796.9  100.56  4854.4   100.6  4864.4  100.54  4879.4   99.81  4891.5  100.64
  4894.9  100.57  4914.5  100.15  4946.3   99.47  4971.8   90.18  4984.2   90.06
  4991.1   86.11  4992.4   85.22  4998.1    83.7  5008.3   84.69  5008.8   86.05
    5014   90.15  5027.1   91.99  5054.6   99.97  5137.2   98.81  5200.6   98.97
  5245.6   99.39  5270.6  100.57  5557.1  100.24
#Mann= 7 , 1 , 0
  4796.9      .2       0  4796.9      .1       0  4894.9     .07       0
  4914.5      .1       0  4946.3     .04       0  5054.6      .1       0
  5557.1      .2       0
Bank Sta=4946.3,5054.6
XS Rating Curve= 0
Exp/Cntr=.3,.1

Type RM Length L Ch R = 1 ,6901.4  ,95.1,92.7,18.2
BEGIN DESCRIPTION:
Cross Section 6901.4-Interpolated
END DESCRIPTION:
XS GIS Cut Line= 6
      3007225.85       13833203.       3007337.5     13831619.29
      3007316.24      13831497.1      3007283.04     13831380.22
      3007256.85     13831318.48       3006989.5     13831016.18
#Sta/Elev= 30
  3289.6  100.98  3465.6   99.49  3481.6    98.2  3561.6   97.32  3977.6   97.28
  4216.4   95.27  4257.6   94.09  4313.6   95.24  4529.6   93.67  4641.6   91.85
  4713.6   92.79  4801.6   97.92  4825.6   98.12  4857.6   96.79  4893.2   93.56
  4909.2   94.69  4925.2   94.21  4979.2   89.62  4985.8   84.77  5009.9   83.92
  5014.3   84.81  5016.5   88.75  5017.3    90.7  5049.3   94.79  5113.3   94.74
  5146.8      96  5178.8   94.96  5413.1   94.86  5517.8   94.57  5593.4   97.78
#Mann= 6 , 1 , 0
  3289.6      .2       0  3289.6      .1       0  4216.4     .07       0
  4979.2     .04       0  5016.5     .07       0  5413.1     .08       0
#XS Ineff= 2 , 0
       0  4825.6   98.12  5146.8       0      96
Permanent Ineff=
       F       F
Bank Sta=4979.2,5016.5
XS Rating Curve= 0
Exp/Cntr=.5,.3

Type RM Length L Ch R = 1 ,6808.7  ,35.8,35.8,35.8
BEGIN DESCRIPTION:
Upstream Section of Bridge/Culvert/Weir
END DESCRIPTION:
XS GIS Cut Line= 6
       3007494.8     13833147.45      3007421.99     13831595.53
      3007418.37     13831551.51       3007395.7     13831437.41
      3007351.84     13831348.55      3007002.77     13831008.56
#Sta/Elev= 30
  3326.1  100.46  3478.1  100.01  3518.1   98.32  3567.5   98.76  3598.1   97.62
  3798.1   96.64  3942.1   96.52  4078.1   97.67  4414.1   93.95  4646.1   94.66
  4742.1   90.99  4798.1   91.54  4920.1    97.1    4938   93.06  4970.4   88.27
  4979.2   89.64  4985.8   84.79  5009.9   83.94  5014.3   84.83  5016.5   88.77
    5037   94.22  5044.6   97.36  5089.4   95.04  5159.4   95.21  5165.2   95.81
  5202.6   94.91  5402.6   95.46  5489.9   94.49  5530.6   94.41  5626.6   97.99
#Mann= 5 , 1 , 0
  3326.1      .1       0  3567.5     .07       0  4979.2     .04       0
  5016.5     .07       0  5489.9     .08       0
#XS Ineff= 2 , 0
       0  4929.4      95  5038.9       0      95
Permanent Ineff=
       F       F
Bank Sta=4979.2,5016.5
XS Rating Curve= 0
Exp/Cntr=.5,.3

Type RM Length L Ch R = 3 ,6790.8  ,,,
BEGIN DESCRIPTION:
ACCESS ROAD
Structure ID: T03-1
END DESCRIPTION:
Bridge Culvert--1,0,-1,-1, 0
Deck Dist Width WeirC Skew NumUp NumDn MinLoCord MaxHiCord MaxSubmerge Is_Ogee
10,15.8,2.6,0, 39, 39, , , .95, 0, 1,1,,
  3326.1  3478.1  3518.1  3566.1  3598.1  3718.1  3798.1  3942.1  4078.1  4414.1
  4622.1  4638.1  4646.1  4734.1  4742.1  4798.1    4866  4886.1  4920.1 4934.81
  4934.9  4972.4  5017.4 5038.49  5038.6  5044.6  5089.4  5159.4  5165.2  5178.6
  5202.6  5386.6  5402.6  5490.6  5506.6  5530.6  5578.6  5602.6  5626.6
  100.46  100.01   98.32   98.81   97.62   97.56   96.64   96.52   97.67   93.95
   94.41    94.7   94.66   91.04   90.99   91.54   95.08   96.06   97.13    97.9
    97.9   98.26   98.28   98.08   98.08   97.41   95.05   95.21   95.81   95.64
   94.91   95.04   95.46   94.48   94.82   94.41   95.95   97.41   97.99
  100.46  100.01   98.32   98.81   97.62   97.56   96.64   96.52   97.67   93.95
   94.41    94.7   94.66   91.04   90.99   91.54   95.08   96.06    97.1   93.78
   96.28   96.64   96.66   96.46   94.88   97.36   95.04   95.21   95.81   95.64
   94.91   95.04   95.46   94.48   94.82   94.41   95.95   97.41   97.99
  3326.1  3478.1  3518.1  3566.1  3598.1  3718.1  3798.1  3942.1  4078.1  4414.1
  4622.1  4638.1  4646.1  4734.1  4742.1  4798.1    4866  4886.1  4920.1 4934.81
  4934.9  4972.4  5017.4 5038.49  5038.6  5044.6  5089.4  5159.4  5165.2  5178.6
  5202.6  5386.6  5402.6  5490.6  5506.6  5530.6  5578.6  5602.6  5626.6
   100.5  100.05   98.36   98.85   97.66    97.6   96.68   96.56   97.71   93.99
   94.45   94.74    94.7   91.08   91.03   91.58   95.12    96.1   97.14    97.9
    97.9   98.26   98.28   98.08   98.08   97.41   95.08   95.25   95.85   95.68
   94.95   95.08    95.5   94.52   94.86   94.45   95.99   97.45   98.03
   100.5  100.05   98.36   98.85   97.66    97.6   96.68   96.56   97.71   93.99
   94.45   94.74    94.7   91.08   91.03   91.58   95.12    96.1   97.14   93.82
   96.32   96.68    96.7    96.5   94.92    97.4   95.08   95.25   95.85   95.68
   94.95   95.08    95.5   94.52   94.86   94.45   95.99   97.45   98.03
Pier Skew, UpSta & Num, DnSta & Num=  ,4970.4, 2 ,4970.4, 2 , 0 , 0 , 0 ,,
       1       1
   87.34   97.63
       1       1
   87.38   97.66
Pier Skew, UpSta & Num, DnSta & Num=  ,5005.5, 2 ,5005.5, 2 , 0 , 0 , 0 ,,
       1       1
   83.25   97.65
       1       1
   83.29   97.69
Abutment Skew #Up #Dn= , 2 , 2
  4934.7  4937.9
   96.28   93.08
  4934.7  4937.9
   96.32   93.12
Abutment Skew #Up #Dn= , 2 , 2
  5036.9 5038.69
   94.19   96.46
  5036.9 5038.69
   94.23    96.5
BR Coef= 1 , 1 , 0 ,1.25, 0 ,,,.8,0,2,0,
WSPro=,,,, 1 ,,,, 0 ,,,, 0 ,,,,-1 ,-1 ,-1 , 0 , 0 , 0 , 0 , 0
BR U #Sta/Elev= 66
  3326.1  100.46  3478.1  100.01  3518.1   98.32  3566.1   98.81  3567.5   98.76
  3598.1   97.62  3718.1   97.56  3798.1   96.64  3942.1   96.52  4078.1   97.67
  4414.1   93.95  4622.1   94.41  4638.1    94.7  4646.1   94.66  4734.1   91.04
  4742.1   90.99  4798.1   91.54  4864.5   94.98    4866   95.08  4886.1   96.06
  4908.5   96.75  4913.5    96.9  4919.5   97.08  4920.1    97.1  4934.7    93.8
 4934.81   93.78  4934.9   93.76    4935   93.74  4937.9   93.08    4938   93.06
  4970.4   88.27  4972.4   88.58  4979.2   89.64  4985.8   84.79  4991.3   84.43
  5000.5   84.42  5005.6   84.28  5009.9   83.94  5014.3   84.83  5016.5   88.77
  5017.4   89.01  5036.9   94.19    5037   94.22 5038.49   94.84  5038.6   94.88
  5038.7   94.92  5044.6   97.36  5044.7   97.35  5055.2   96.81  5070.2   96.03
  5089.4   95.04  5090.2   95.04  5131.3   95.18  5159.4   95.21  5165.2   95.81
  5178.6   95.64  5202.6   94.91  5386.6   95.04  5402.6   95.46  5489.9   94.49
  5490.6   94.48  5506.6   94.82  5530.6   94.41  5578.6   95.95  5602.6   97.41
  5626.6   97.99
BR U #Mann= 5
  3326.1      .1  3567.5     .07  4979.2     .04  5016.5     .07  5489.9     .08
BR U Banks=4979.2,5016.5
BR D #Sta/Elev= 66
  3326.1   100.5  3478.1  100.05  3518.1   98.36  3566.1   98.85  3567.5    98.8
  3598.1   97.66  3718.1    97.6  3798.1   96.68  3942.1   96.56  4078.1   97.71
  4414.1   93.99  4622.1   94.45  4638.1   94.74  4646.1    94.7  4734.1   91.08
  4742.1   91.03  4798.1   91.58  4864.5   95.02    4866   95.12  4886.1    96.1
  4908.5   96.79  4913.5   96.94  4919.5   97.12  4920.1   97.14  4934.7   93.84
 4934.81   93.82  4934.9    93.8    4935   93.78  4937.9   93.12    4938    93.1
  4970.4   88.31  4972.4   88.62  4979.2   89.68  4985.8   84.83  4991.3   84.47
  5000.5   84.46  5005.6   84.32  5009.9   83.98  5014.3   84.87  5016.5   88.81
  5017.4   89.05  5036.9   94.23    5037   94.26 5038.49   94.88  5038.6   94.92
  5038.7   94.96  5044.6    97.4  5044.7   97.39  5055.2   96.85  5070.2   96.07
  5089.4   95.08  5090.2   95.08  5131.3   95.22  5159.4   95.25  5165.2   95.85
  5178.6   95.68  5202.6   94.95  5386.6   95.08  5402.6    95.5  5489.9   94.53
  5490.6   94.52  5506.6   94.86  5530.6   94.45  5578.6   95.99  5602.6   97.45
  5626.6   98.03
BR D #Mann= 5
  3326.1      .1  3567.5     .07  4979.2     .04  5016.5     .07  5489.9     .08
BR D Banks=4979.2,5016.5
BC Design=,, 0 ,, 0 ,,,,,,
BC HTab HWMax=100.46

Type RM Length L Ch R = 1 ,6772.9  ,413.8,413.8,413.8
BEGIN DESCRIPTION:
Downstream Section of Bridge/Culvert/Weir
END DESCRIPTION:
XS GIS Cut Line= 6
      3007529.78     13833139.83      3007456.97     13831587.91
      3007453.35     13831543.89      3007430.68     13831429.79
      3007386.82     13831340.93      3007037.75     13831000.94
#Sta/Elev= 30
  3326.1  100.51  3478.1  100.06  3518.1   98.37  3567.5   98.81  3598.1   97.67
  3798.1   96.69  3942.1   96.57  4078.1   97.72  4414.1      94  4646.1   94.71
  4742.1   91.04  4798.1   91.59  4920.1   97.15    4938   93.11  4970.4   88.32
  4979.2   89.69  4985.8   84.84  5009.9   83.99  5014.3   84.88  5016.5   88.82
    5037   94.27  5044.6   97.41  5089.4   95.09  5159.4   95.26  5165.2   95.86
  5202.6   94.96  5402.6   95.51  5489.9   94.54  5530.6   94.46  5626.6   98.04
#Mann= 5 , 1 , 0
  3326.1      .1       0  3567.5     .07       0  4979.2     .04       0
  5016.5     .07       0  5489.9     .08       0
#XS Ineff= 2 , 0
       0  4929.4      95  5038.9       0      95
Permanent Ineff=
       F       F
Bank Sta=4979.2,5016.5
XS Rating Curve= 0
Exp/Cntr=.5,.3

Type RM Length L Ch R = 1 ,6359.1  ,0,0,0
BEGIN DESCRIPTION:
Cross Section 6359.1-Interpolated
END DESCRIPTION:
XS GIS Cut Line= 6
      3007647.17     13833450.53      3007843.51     13831604.58
       3007839.2     13831382.52      3007772.37     13831136.74
      3007634.39     13830947.02      3007300.55     13830642.45
#Sta/Elev= 30
  2917.2   101.1  3088.5     100  3118.7      99  3330.1    99.8  3384.1    98.1
  3495.8    96.5  3767.3      97  3978.5    95.7  4053.9      94  4265.1    93.6
  4310.3    92.2    4431    94.7  4596.9    92.8  4697.4    93.2  4780.7    95.2
  4908.5   95.13  4927.9    94.3    4958    89.1  4972.1    88.6  4985.8   85.06
  5009.9   84.21  5014.3    85.1  5018.3      89  5033.5    93.2  5048.6    94.3
  5222.8    93.4  5289.6    95.6  5364.6    94.2  5908.5   95.95  5937.9    96.6
#Mann= 5 , 1 , 0
  2917.2      .2       0  4908.5     .07       0    4958     .04       0
  5018.3     .07       0  5908.5      .2       0
#XS Ineff= 2 , 0
       0    4898    95.2  5290.4       0    95.6
Permanent Ineff=
       F       F
Bank Sta=4958,5018.3
XS Rating Curve= 0
Exp/Cntr=.3,.1

Chan Stop Cuts=-1